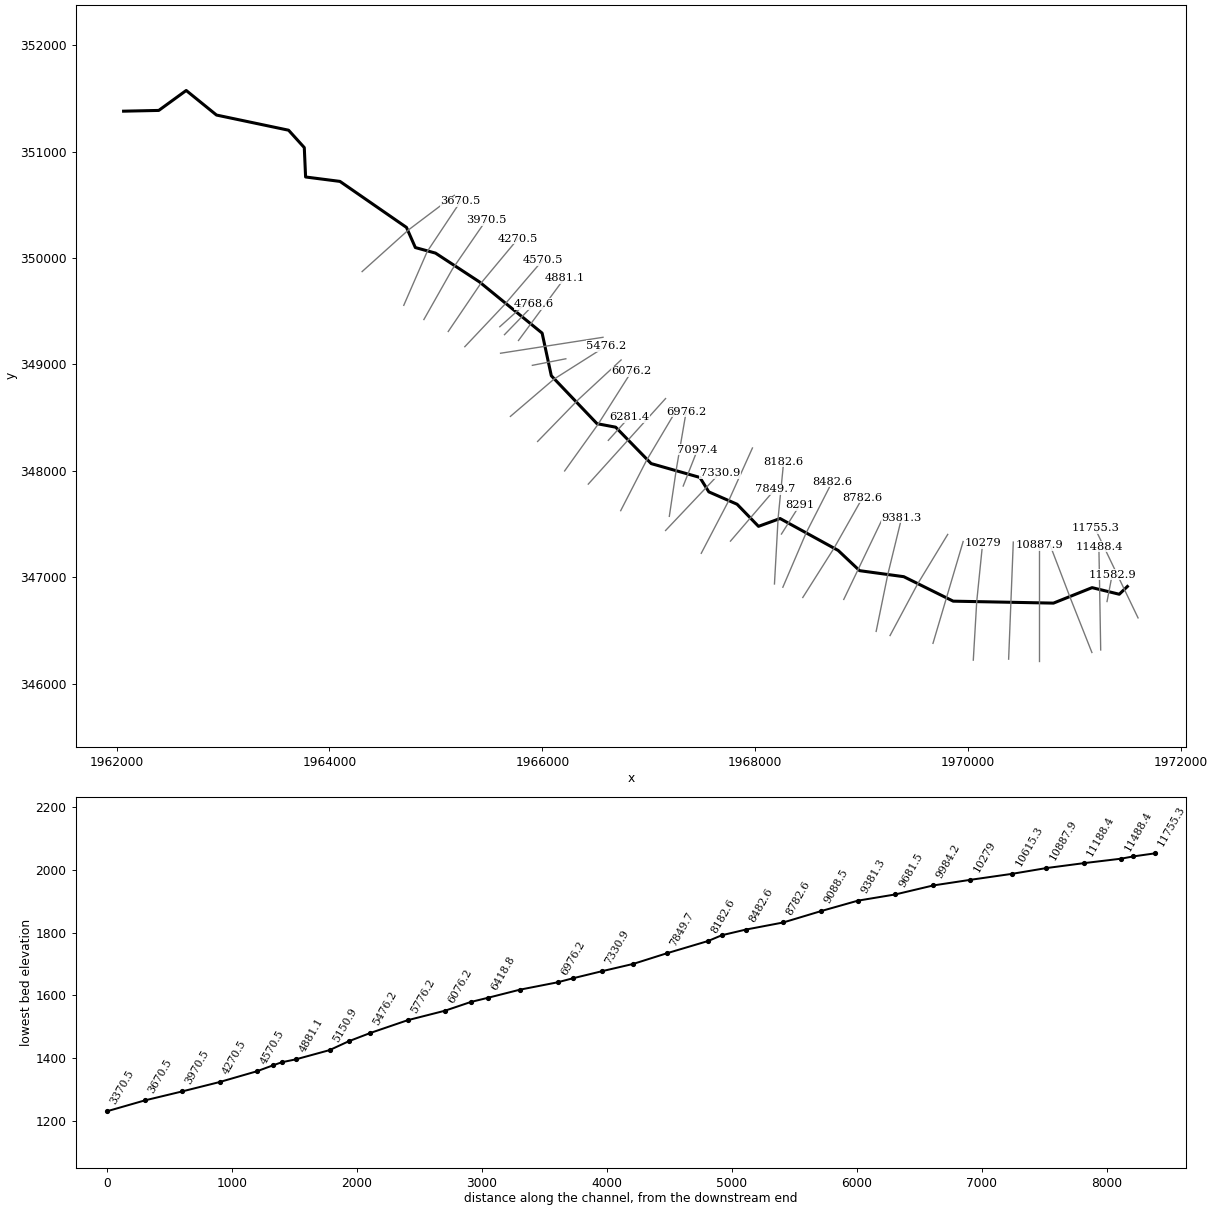
--- EphrmCrk.prj (project) ---

Proj Title=EphrmCrk
Current Plan=p01
Geom File=g01
Flow File=f01
Plan File=p01
DSS Export Rating Curves=0
DSS Export Rating Curve Sorted=0
DSS Export Volume Flow Curves=0
DXF OffsetX=0
DXF OffsetY=0
DXF ScaleX=0
DXF ScaleY=0

--- EphrmCrk.p01 (plan) ---

Plan Title=Floodplain
Program Version=4.00
Geom File=g01
Flow File=f01
K Sum by GR=0
Std Step Tol=0.01
Critical Tol=0.01
Num of Std Step Trials=20
Max Error Tol=0.3
Flow Tol Ratio=0.001
Split Flow NTrial=30
Split Flow Tol=0.02
Split Flow Ratio=0.02
Log Output Level=0
Friction Slope Method=1
Unsteady Friction Slope Method=2
Unsteady Bridges Friction Slope Method=1
Global Log Level=0
CheckData=False
Run HTab=0
Run UNet=0
Run PostProcess=0
UNET Theta=0
UNET Theta Warmup=0
UNET ZTol=0
UNET ZSATol=0
UNET MxIter=0
UNET MaxInSteps=0
UNET DtIC=0
UNET DtMin=0
UNET MaxCRTS=0
UNET WFStab=0
UNET SFStab=0
UNET WFX=0
UNET SFX=0
UNET DSS MLevel=0
UNET DZMax Abort=0
UNET Convert EG Bridges=0
UNET Use Existing IB Tables=0
UNET Froude Limit=0
UNET Froude Power=0
Write IC File=0
Echo Input=False
Echo Output=False
Write Detailed=0

--- EphrmCrk.f01 (steady flow) ---

Flow Title=NFF Regression Equation
Program Version=4.00
Number of Profiles=1
Profile Names=P100yr
River Rch & RM=EphrmCrk,Main      ,11755.3
399.6751
River Rch & RM=EphrmCrk,Main      ,11582.9
399.6751
River Rch & RM=EphrmCrk,Main      ,11188.4
608.0019
River Rch & RM=EphrmCrk,Main      ,9381.3
646.5543
River Rch & RM=EphrmCrk,Main      ,6676.2
707.2399
River Rch & RM=EphrmCrk,Main      ,4768.6
779.2011
River Rch & RM=EphrmCrk,Main      ,1915.6
864.5387
River Rch & RM=EphrmCrk,Main      ,1564.7
1145.155
Boundary for River Rch & Prof#=EphrmCrk,Main      ,1
Up Type=0
Dn Type=3
Dn Slope=0.062989

--- EphrmCrk.g01 (geometry) ---

Geom Title=USGS 3m DEM
Program Version=4.00

River Reach=EphrmCrk     ,Main
Reach XY= 30
     1971495.943      346913.889     1971419.554      346840.972
     1971164.253      346903.015     1970801.498      346757.639
     1969859.443      346775.982     1969395.248      347005.902
     1968980.218      347062.453     1968778.929      347252.430
     1968233.076      347552.333     1968030.382      347478.798
     1967829.276      347686.458     1967563.651      347802.777
     1967479.508      347938.352     1967021.984      348068.402
     1966688.651      348410.416     1966513.304      348443.402
     1966083.966      348893.677     1965997.679      349294.097
     1965409.137      349775.000     1964995.943      350045.833
     1964806.706      350097.916     1964723.373      350287.152
     1964098.373      350719.444     1963775.618      350760.922
     1963763.304      351037.152     1963615.734      351200.347
     1962938.651      351342.708     1962653.964      351573.595
     1962396.166      351386.192     1962065.741      351379.127

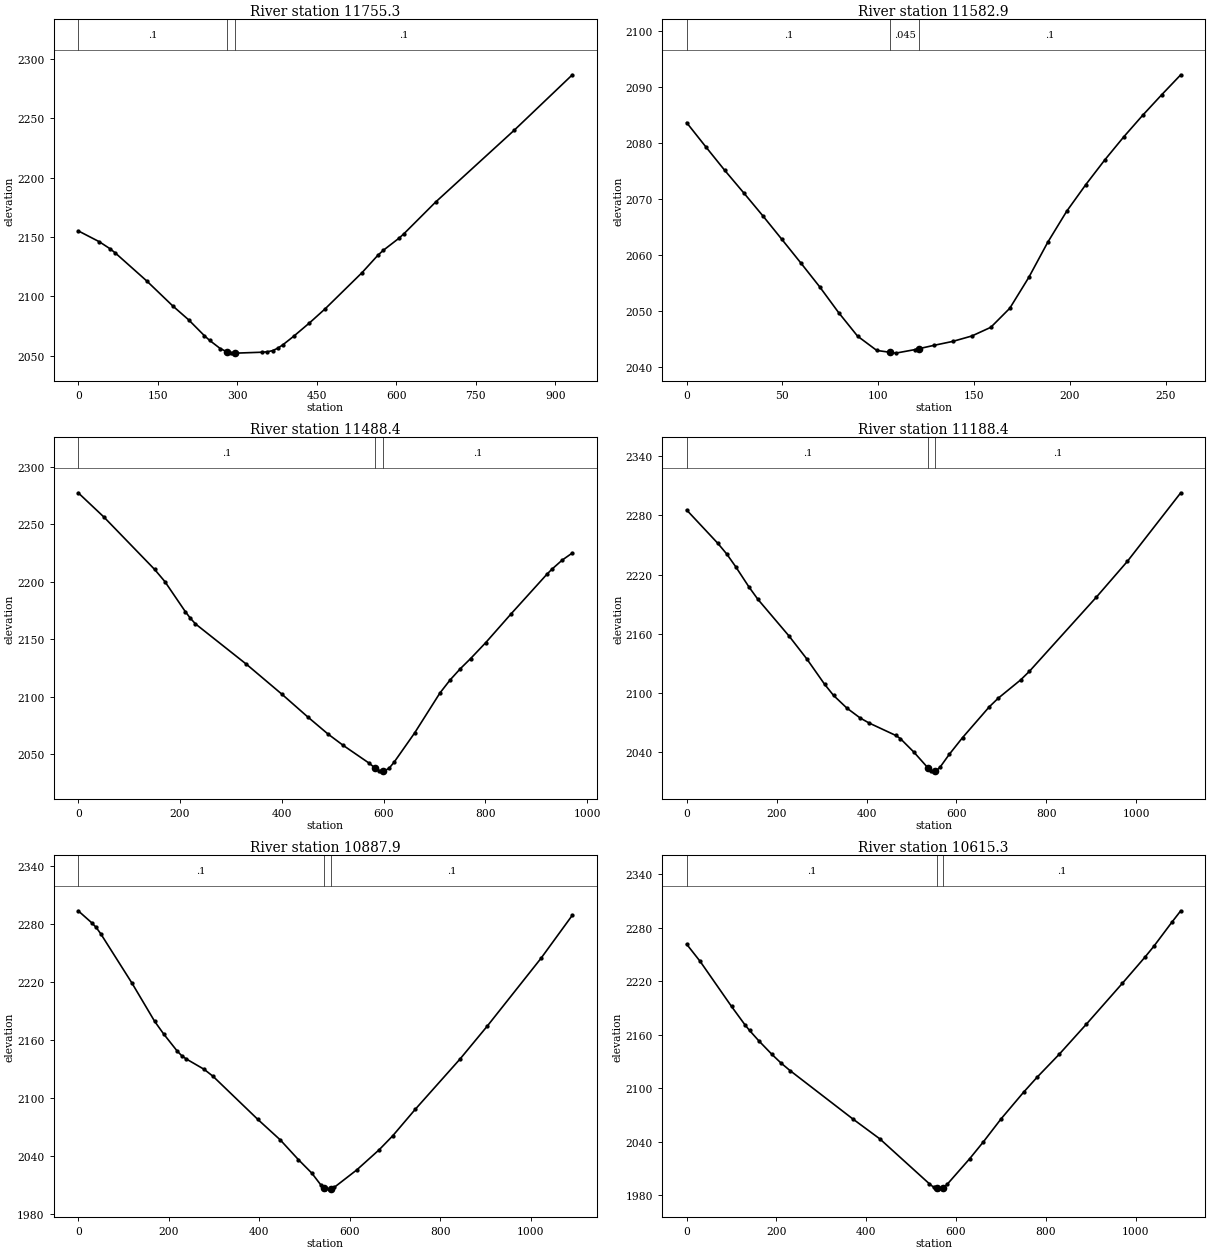
Type RM Length L Ch R = 1 ,11755.3,185.7,172.3,158.7
XS GIS Cut Line= 2
     1971596.085      346618.773     1971192.418      347458.994
#Sta/Elev= 30
       0 2155.23    39.7 2146.07    59.5 2140.30    69.4 2136.80   128.9 2113.13
   178.5 2091.86   208.2 2080.25   238.0 2066.84   247.9 2062.88   267.8 2056.02
   280.5 2053.26   287.6 2052.44   295.5 2052.19   297.5 2052.13   347.1 2052.90
   357.0 2053.28   366.9 2054.26   376.8 2056.36   386.8 2059.40   406.6 2066.39
   436.3 2077.60   466.1 2089.59   535.5 2120.02   565.2 2134.59   575.2 2138.69
   604.9 2148.93   614.8 2152.94   674.3 2179.53   823.1 2240.30   932.2 2286.81
#Mann= 3 , 0 , 0
       0     0.1       0   280.5   0.045       0   295.5     0.1       0
Bank Sta=   280.5,   295.5
Exp/Cntr=0.3,0.1

Type RM Length L Ch R = 1 ,11582.9,90.1,94.5,99.1
XS GIS Cut Line= 2
     1971304.622      346772.474     1971353.269      347025.685
#Sta/Elev= 29
       0 2083.61     9.9 2079.33    19.8 2075.12    29.8 2071.06    39.7 2066.99
    49.6 2062.80    59.5 2058.58    69.4 2054.29    79.3 2049.68    89.2 2045.47
    99.2 2042.92   106.3 2042.58   109.1 2042.44   119.0 2043.06   121.3 2043.24
   128.9 2043.82   138.8 2044.53   148.8 2045.50   158.7 2047.05   168.6 2050.45
   178.5 2055.95   188.4 2062.23   198.3 2067.78   208.3 2072.55   218.2 2076.96
   228.1 2081.08   238.0 2084.94   247.9 2088.60   257.8 2092.15
#Mann= 3 , 0 , 0
       0     0.1       0   106.3   0.045       0   121.3     0.1       0
Bank Sta=   106.3,   121.3
Exp/Cntr=0.3,0.1

Type RM Length L Ch R = 1 ,11488.4,291.8,299.9,307.7
XS GIS Cut Line= 3
     1971245.098      346317.698     1971235.044      346908.540
     1971227.980      347288.459
#Sta/Elev= 30
       0 2277.46    50.1 2256.55   150.2 2210.78   170.3 2200.23   210.3 2174.21
   220.4 2168.34   230.4 2163.44   330.5 2128.36   400.6 2102.15   450.7 2082.65
   490.8 2067.66   520.8 2057.75   570.9 2042.54   583.4 2038.06   590.9 2035.89
   598.4 2035.52   600.9 2035.39   610.9 2037.88   620.9 2043.28   660.9 2068.50
   710.9 2103.44   730.9 2114.78   750.9 2124.51   770.9 2133.23   800.9 2147.22
   850.9 2172.34   920.9 2206.60   930.9 2211.06   950.9 2218.90   970.9 2225.12
#Mann= 3 , 0 , 0
       0     0.1       0   583.4   0.045       0   598.4     0.1       0
Bank Sta=   583.4,   598.4
Exp/Cntr=0.3,0.1

Type RM Length L Ch R = 1 ,11188.4,309,300.4,292.2
XS GIS Cut Line= 3
     1971162.537      346293.699     1970962.048      346799.983
     1970763.993      347317.713
#Sta/Elev= 30
       0 2285.44    69.3 2251.71    89.1 2240.92   108.9 2228.14   138.6 2207.51
   158.4 2195.02   227.7 2157.85   267.3 2134.63   306.9 2108.95   326.7 2097.72
   356.4 2084.87   386.1 2074.80   405.9 2069.75   465.3 2057.15   475.2 2054.05
   504.9 2040.54     537 2024.17   544.5 2021.19     552 2021.10   554.4 2021.07
   564.3 2025.51   584.1 2038.08   613.8 2055.11   673.2 2086.24   693.0 2094.92
   742.5 2113.30   762.3 2122.12   910.8 2196.99   980.1 2233.40  1098.8 2302.81
#Mann= 3 , 0 , 0
       0     0.1       0     537   0.045       0     552     0.1       0
Bank Sta=     537,     552
Exp/Cntr=0.3,0.1

Type RM Length L Ch R = 1 ,10887.9,273.3,272.5,271.6
XS GIS Cut Line= 3
     1970669.514      346211.639     1970669.514      346757.639
     1970669.514      347303.639
#Sta/Elev= 30
       0 2294.02    29.8 2281.62    39.7 2276.76    49.6 2270.30   119.1 2218.78
   168.8 2179.45   188.6 2166.43   218.4 2148.75   228.3 2143.96   238.3 2140.51
   278.0 2129.71   297.8 2122.45   397.1 2077.61   446.7 2056.36   486.4 2036.08
   516.2 2022.00   536.1 2009.80   543.8 2006.83   546.0 2005.98   555.9 2005.39
   558.8 2005.93   565.9 2007.26   615.5 2025.27   665.1 2046.21   694.9 2060.59
   744.6 2088.01   843.8 2140.30   903.4 2174.11  1022.5 2244.60  1092.0 2289.40
#Mann= 3 , 0 , 0
       0     0.1       0   543.8   0.045       0   558.8     0.1       0
Bank Sta=   543.8,   558.8
Exp/Cntr=0.3,0.1

Type RM Length L Ch R = 1 ,10615.3,336.4,335.8,334.4
XS GIS Cut Line= 2
     1970380.287      346231.312     1970424.011      347330.874
#Sta/Elev= 30
       0 2261.77    30.0 2242.55   100.0 2191.94   130.0 2171.28   140.0 2165.11
   160.1 2153.78   190.1 2138.14   210.1 2128.56   230.1 2120.13   370.1 2065.84
   430.2 2043.51   540.2 1993.30   550.2 1989.22   556.5 1987.91   560.2 1987.14
   570.2 1988.19   571.5 1988.75   580.2 1992.48   630.2 2021.14   660.3 2039.78
   700.3 2065.92   750.3 2095.70   780.3 2112.47   830.3 2138.61   890.4 2172.17
   970.4 2217.88  1020.4 2247.03  1040.4 2259.33  1080.4 2286.21  1100.4 2299.18
#Mann= 3 , 0 , 0
       0     0.1       0   556.5   0.045       0   571.5     0.1       0
Bank Sta=   556.5,   571.5
Exp/Cntr=0.3,0.1

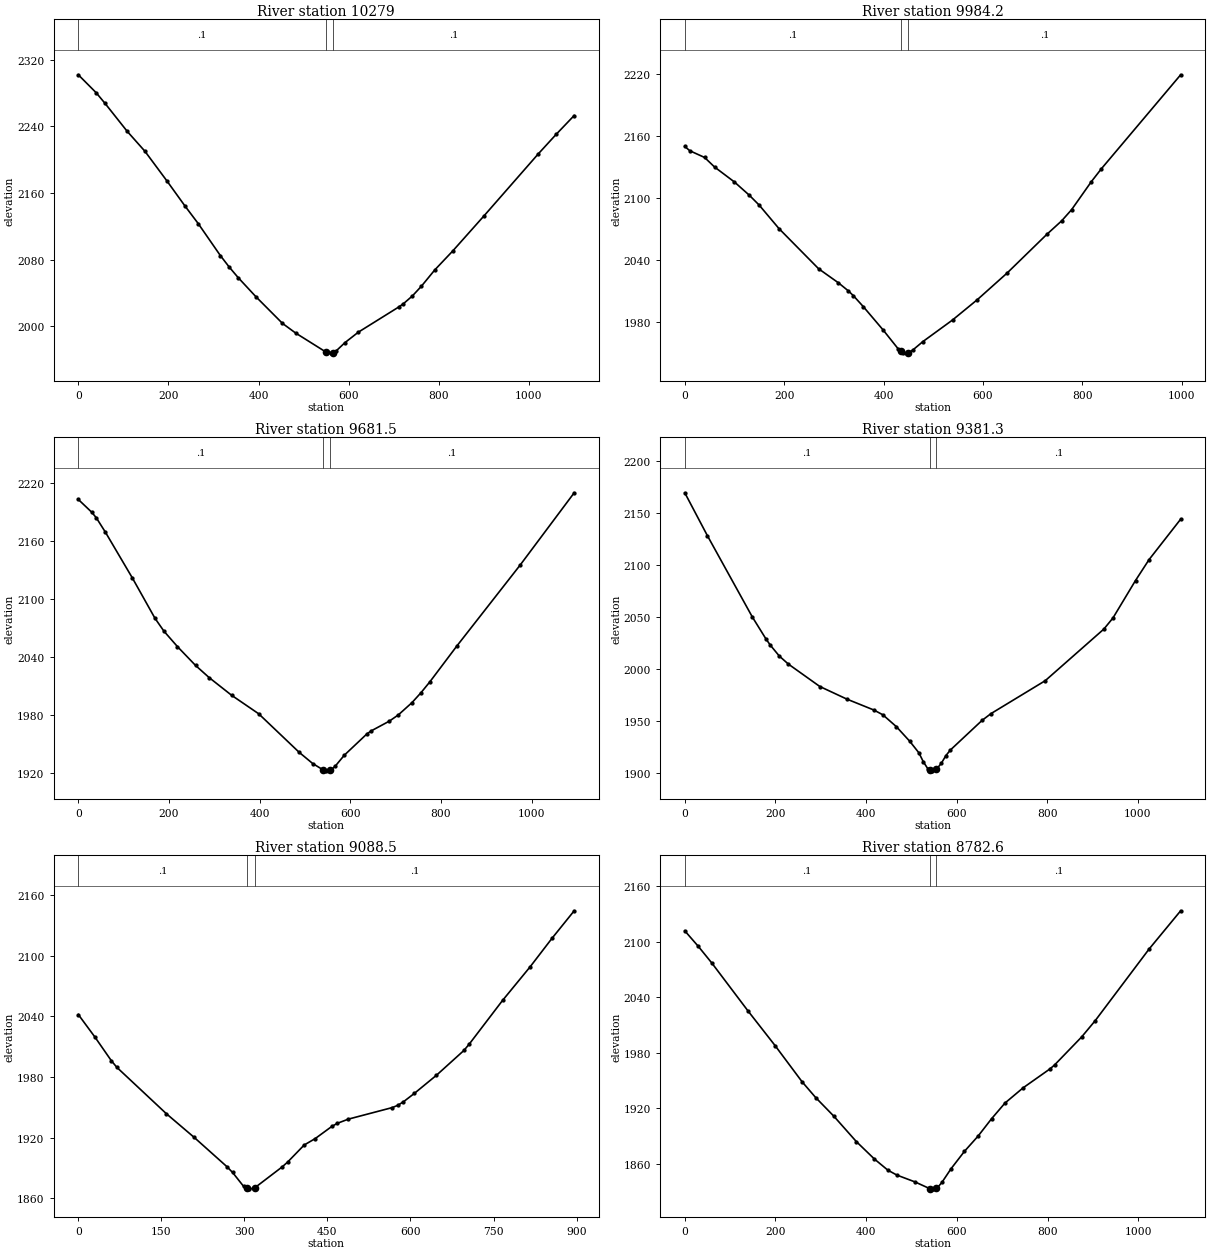
Type RM Length L Ch R = 1 ,10279,300,294.9,290.7
XS GIS Cut Line= 3
     1970048.312      346222.063     1970080.553      346772.764
     1970135.943      347318.863
#Sta/Elev= 30
       0 2302.01    39.4 2280.64    59.1 2267.86   108.4 2234.23   147.8 2210.27
   197.0 2174.39   236.4 2144.79   266.0 2123.54   315.2 2085.11   334.9 2071.28
   354.6 2058.70   394.0 2035.76   453.1 2003.66   482.7 1991.94   549.3 1969.36
   561.6 1967.97   564.3 1968.59   571.6 1970.28   591.6 1980.49   621.5 1993.13
   711.3 2023.38   721.3 2027.16   741.3 2036.54   761.2 2048.12   791.2 2067.87
   831.1 2090.63   900.9 2133.03  1020.7 2207.02  1060.6 2230.59  1100.5 2253.15
#Mann= 3 , 0 , 0
       0     0.1       0   549.3   0.045       0   564.3     0.1       0
Bank Sta=   549.3,   564.3
Exp/Cntr=0.3,0.1

Type RM Length L Ch R = 1 ,9984.2,307.1,302.5,296.7
XS GIS Cut Line= 2
     1969669.630      346379.837     1969952.954      347336.226
#Sta/Elev= 30
       0 2150.33    10.0 2146.16    39.9 2139.62    59.8 2130.43    99.8 2115.92
   129.7 2103.12   149.6 2093.54   189.5 2070.77   269.3 2031.84   309.2 2018.21
   329.2 2010.40   339.1 2005.83   359.1 1995.22   399.0 1972.60   428.9 1954.56
   434.8 1952.06   438.9 1950.32   448.9 1950.19   449.8 1950.47   458.8 1953.22
   478.8 1961.30   538.6 1982.26   588.5 2001.95   648.4 2027.72   728.2 2065.13
   758.1 2078.24   778.0 2088.99   817.9 2116.23   837.9 2128.61   997.5 2219.66
#Mann= 3 , 0 , 0
       0     0.1       0   434.8   0.045       0   449.8     0.1       0
Bank Sta=   434.8,   449.8
Exp/Cntr=0.3,0.1

Type RM Length L Ch R = 1 ,9681.5,293.4,300,307
XS GIS Cut Line= 3
     1969266.232      346452.980     1969524.131      346935.476
     1969808.029      347403.056
#Sta/Elev= 30
       0 2202.50    29.8 2189.22    39.8 2183.45    59.7 2168.72   119.4 2121.22
   169.1 2079.68   189.0 2066.28   218.8 2050.33   258.6 2030.94   288.5 2018.40
   338.2 2000.06   397.9 1980.95   487.4 1941.03   517.2 1929.47   539.6 1923.08
   547.1 1921.63   554.6 1922.40   557.0 1922.65   567.0 1926.82   586.9 1938.08
   636.6 1960.04   646.6 1963.32   686.3 1973.32   706.2 1979.79   736.1 1992.39
   756.0 2002.65   775.8 2014.02   835.5 2051.16   974.8 2134.61  1094.1 2209.38
#Mann= 3 , 0 , 0
       0     0.1       0   539.6   0.045       0   554.6     0.1       0
Bank Sta=   539.6,   554.6
Exp/Cntr=0.3,0.1

Type RM Length L Ch R = 1 ,9381.3,298.3,292.7,287.9
XS GIS Cut Line= 3
     1969135.708      346492.072     1969245.233      347027.557
     1969375.294      347559.958
#Sta/Elev= 30
       0 2169.78    49.7 2128.66   149.1 2050.23   178.9 2029.28   188.8 2023.10
   208.7 2012.58   228.6 2004.89   298.1 1983.29   357.8 1971.15   417.4 1960.65
   437.3 1956.03   467.1 1944.62   496.9 1930.41   516.8 1919.42   526.7 1910.72
   536.6 1904.04   540.3 1903.21   546.6 1901.81   555.3 1903.45   566.5 1909.51
   576.5 1916.81   586.4 1922.18   656.2 1950.65   676.1 1957.23   795.7 1988.88
   925.2 2038.62   945.2 2049.26   995.0 2085.36  1024.9 2105.46  1094.6 2144.35
#Mann= 3 , 0 , 0
       0     0.1       0   540.3   0.045       0   555.3     0.1       0
Bank Sta=   540.3,   555.3
Exp/Cntr=0.3,0.1

Type RM Length L Ch R = 1 ,9088.5,308.3,305.6,304.1
XS GIS Cut Line= 2
     1968831.414      346792.293     1969218.745      347599.889
#Sta/Elev= 30
       0 2041.79    29.9 2019.55    59.7 1996.02    69.7 1989.44   159.2 1943.49
   209.0 1920.24   268.7 1890.97   278.6 1885.40   298.6 1871.57   304.1 1870.06
   308.5 1868.86   319.1 1870.34   368.2 1890.86   378.2 1895.72   408.0 1912.56
   427.9 1918.92   457.8 1930.92   467.7 1934.00   487.6 1938.17   567.3 1949.67
   577.2 1951.93   587.2 1955.34   607.1 1963.72   646.9 1981.64   696.6 2006.26
   706.6 2012.83   766.3 2055.76   816.1 2089.04   855.9 2117.48   895.7 2144.55
#Mann= 3 , 0 , 0
       0     0.1       0   304.1   0.045       0   319.1     0.1       0
Bank Sta=   304.1,   319.1
Exp/Cntr=0.3,0.1

Type RM Length L Ch R = 1 ,8782.6,296.4,299.9,300.9
XS GIS Cut Line= 3
     1968446.559      346810.496     1968739.379      347272.996
     1969008.187      347748.411
#Sta/Elev= 30
       0 2111.53    29.9 2094.69    59.7 2076.69   139.3 2025.02   199.1 1987.50
   258.8 1948.28   288.6 1931.34   328.4 1911.32   378.2 1883.78   418.0 1864.94
   447.9 1852.79   467.8 1847.48   507.6 1840.12   539.9 1832.91   547.4 1832.30
   554.9 1833.51   557.3 1833.90   567.3 1839.73   587.1 1854.26   616.9 1873.21
   646.7 1889.53   676.5 1908.33   706.3 1925.40   746.0 1941.74   805.6 1962.34
   815.5 1966.50   875.1 1996.72   904.9 2014.24  1024.0 2091.83  1093.6 2133.17
#Mann= 3 , 0 , 0
       0     0.1       0   539.9   0.045       0   554.9     0.1       0
Bank Sta=   539.9,   554.9
Exp/Cntr=0.3,0.1

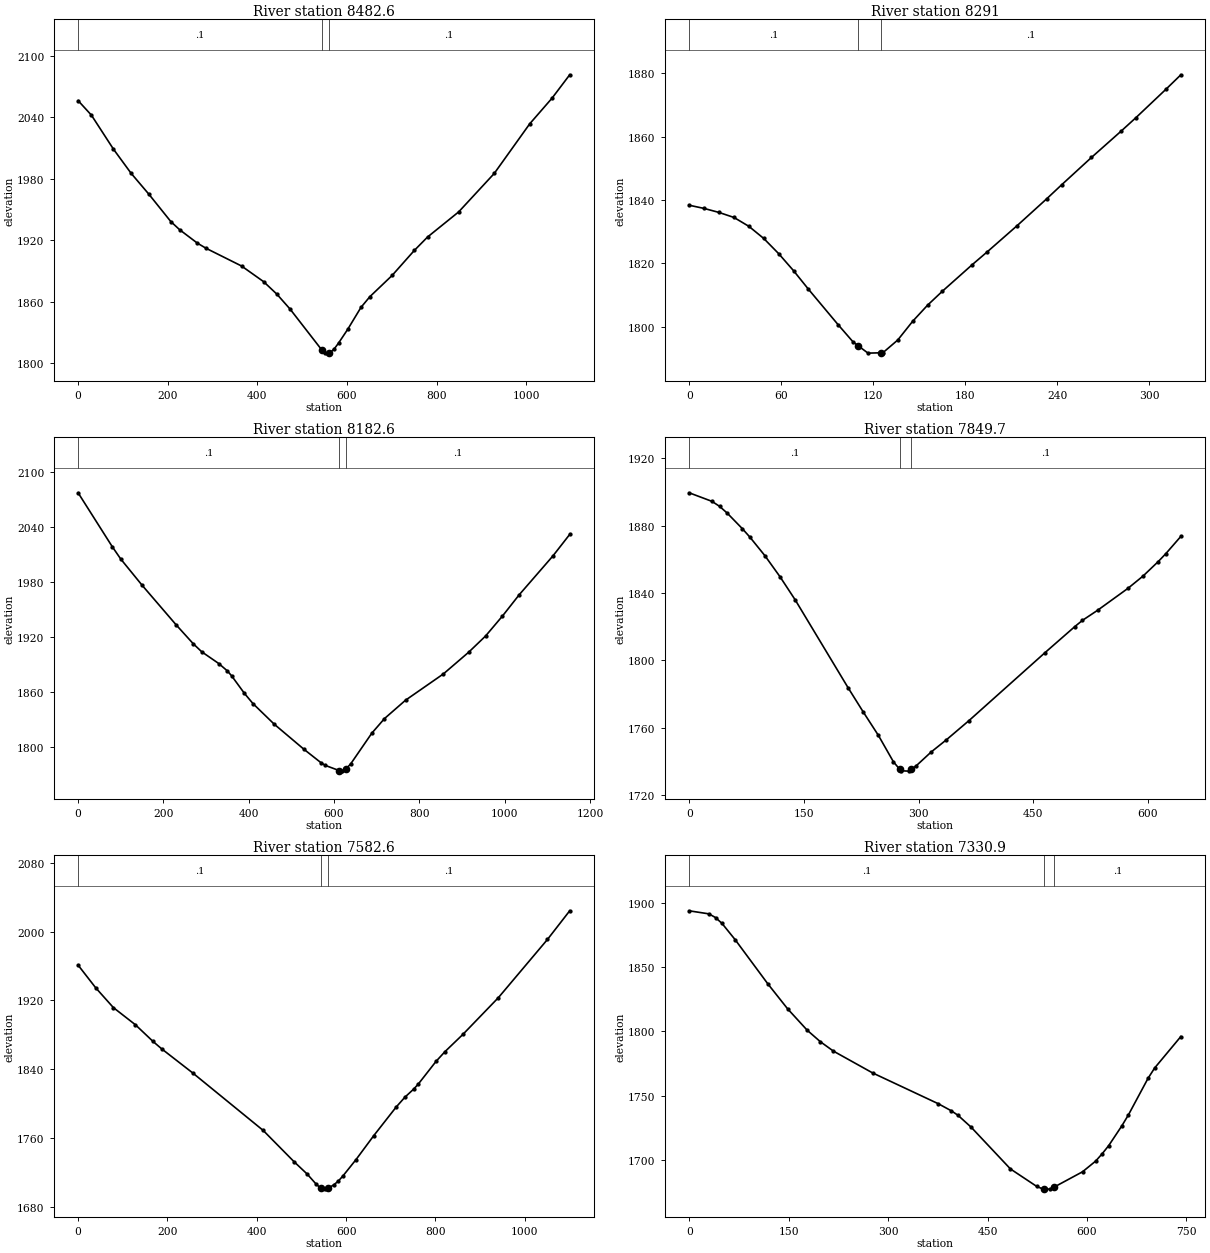
Type RM Length L Ch R = 1 ,8482.6,195.1,191.5,189.4
XS GIS Cut Line= 3
     1968259.202      346906.915     1968476.555      347414.224
     1968723.884      347899.888
#Sta/Elev= 30
       0 2056.20    29.6 2042.06    78.8 2008.85   118.3 1985.20   157.7 1964.91
   207.0 1938.02   226.7 1930.07   266.1 1917.03   285.8 1911.92   364.6 1894.71
   413.9 1879.41   443.5 1867.20   473.1 1852.55   544.4 1812.33   551.9 1809.60
   559.4 1809.81   561.8 1809.88   571.7 1813.82   581.6 1819.72   601.5 1832.78
   631.2 1854.29   651.0 1864.73   700.6 1885.43   750.1 1909.84   779.8 1923.02
   849.2 1947.54   928.5 1985.06  1007.7 2033.54  1057.3 2058.50  1096.9 2081.41
#Mann= 3 , 0 , 0
       0     0.1       0   544.4   0.045       0   559.4     0.1       0
Bank Sta=   544.4,   559.4
Exp/Cntr=0.3,0.1

Type RM Length L Ch R = 1 ,8291,96.8,108.4,118.9
XS GIS Cut Line= 2
     1968245.993      347406.541     1968417.295      347677.631
#Sta/Elev= 29
       0 1838.37     9.7 1837.36    19.4 1836.10    29.2 1834.51    38.9 1831.71
    48.6 1827.88    58.3 1823.10    68.0 1817.73    77.7 1811.89    97.2 1800.61
   106.9 1795.21   110.3 1793.98   116.6 1791.69   125.3 1791.80   126.3 1791.81
   136.0 1795.82   145.8 1801.77   155.5 1806.84   165.2 1811.26   184.6 1819.61
   194.4 1823.66   213.8 1831.89   233.2 1840.41   242.9 1844.81   262.4 1853.46
   281.8 1861.79   291.5 1866.06   311.0 1874.99   320.7 1879.54
#Mann= 3 , 0 , 0
       0     0.1       0   110.3   0.045       0   125.3     0.1       0
Bank Sta=   110.3,   125.3
Exp/Cntr=0.3,0.1

Type RM Length L Ch R = 1 ,8182.6,347.9,332.7,318.4
XS GIS Cut Line= 3
     1968180.337      346937.446     1968214.719      347556.149
     1968266.951      348086.461
#Sta/Elev= 30
       0 2077.16    80.0 2018.43    99.9 2004.96   149.9 1976.38   229.9 1933.06
   269.8 1912.54   289.8 1903.71   329.8 1890.87   349.8 1882.88   359.8 1877.54
   389.8 1858.40   409.8 1847.25   459.8 1824.70   529.7 1797.24   569.7 1782.57
   579.7 1779.69   612.2 1774.09   619.7 1773.49   627.2 1775.41   639.4 1781.62
   688.7 1814.97   718.3 1830.83   767.7 1850.89   856.5 1879.60   915.7 1903.25
   955.2 1920.88   994.6 1942.55  1034.1 1965.90  1113.1 2008.25  1152.5 2031.74
#Mann= 3 , 0 , 0
       0     0.1       0   612.2   0.045       0   627.2     0.1       0
Bank Sta=   612.2,   627.2
Exp/Cntr=0.3,0.1

Type RM Length L Ch R = 1 ,7849.7,261.6,266.8,273.3
XS GIS Cut Line= 2
     1967767.012      347340.016     1968186.120      347827.867
#Sta/Elev= 30
       0 1899.52    29.7 1894.45    39.6 1891.50    49.5 1887.53    69.3 1878.28
    79.2 1873.26    99.0 1862.14   118.7 1849.67   138.5 1835.98   207.8 1783.69
   227.6 1769.31   247.4 1755.41   267.2 1739.62   275.1 1735.36   277.0 1734.33
   287.0 1734.13   290.1 1735.11   296.8 1737.24   316.6 1745.53   336.4 1752.73
   366.1 1764.20   465.0 1804.35   504.6 1820.08   514.5 1823.74   534.3 1829.72
   573.9 1842.72   593.7 1850.04   613.5 1858.60   623.4 1863.29   643.2 1873.61
#Mann= 3 , 0 , 0
       0     0.1       0   275.1   0.045       0   290.1     0.1       0
Bank Sta=   275.1,   290.1
Exp/Cntr=0.3,0.1

Type RM Length L Ch R = 1 ,7582.6,258.1,251.8,244.2
XS GIS Cut Line= 3
     1967492.568      347225.555     1967748.336      347715.174
     1967973.456      348215.047
#Sta/Elev= 30
       0 1961.05    39.5 1934.63    78.9 1911.70   128.2 1891.75   167.7 1872.33
   187.4 1863.57   256.5 1835.70   414.3 1768.83   483.4 1732.46   512.9 1718.03
   532.7 1706.47   542.5 1701.93   544.9 1701.59   552.4 1700.52   559.9 1701.72
   572.3 1705.43   582.3 1709.76   592.3 1715.46   622.2 1734.88   662.0 1762.78
   711.9 1795.88   731.8 1807.53   751.8 1817.12   761.7 1822.78   801.6 1849.27
   821.5 1860.52   861.4 1880.45   941.1 1923.34  1050.8 1990.94  1100.6 2024.26
#Mann= 3 , 0 , 0
       0     0.1       0   544.9   0.045       0   559.9     0.1       0
Bank Sta=   544.9,   559.9
Exp/Cntr=0.3,0.1

Type RM Length L Ch R = 1 ,7330.9,224.6,233.5,242.3
XS GIS Cut Line= 2
     1967157.418      347439.897     1967667.225      347978.657
#Sta/Elev= 30
       0 1893.81    29.7 1891.44    39.6 1888.56    49.4 1884.00    69.2 1871.36
   118.7 1836.84   148.4 1817.50   178.0 1800.81   197.8 1791.89   217.6 1784.54
   276.9 1767.52   375.8 1743.59   395.6 1738.04   405.5 1734.58   425.3 1725.34
   484.6 1692.82   524.2 1679.24   534.0 1677.11   535.7 1677.11   543.9 1677.13
   550.7 1678.74   593.4 1690.62   613.2 1698.95   623.0 1704.63   632.9 1711.03
   652.7 1726.39   662.6 1734.91   692.3 1763.48   702.2 1771.44   741.7 1795.92
#Mann= 3 , 0 , 0
       0     0.1       0   535.7   0.045       0   550.7     0.1       0
Bank Sta=   535.7,   550.7
Exp/Cntr=0.3,0.1

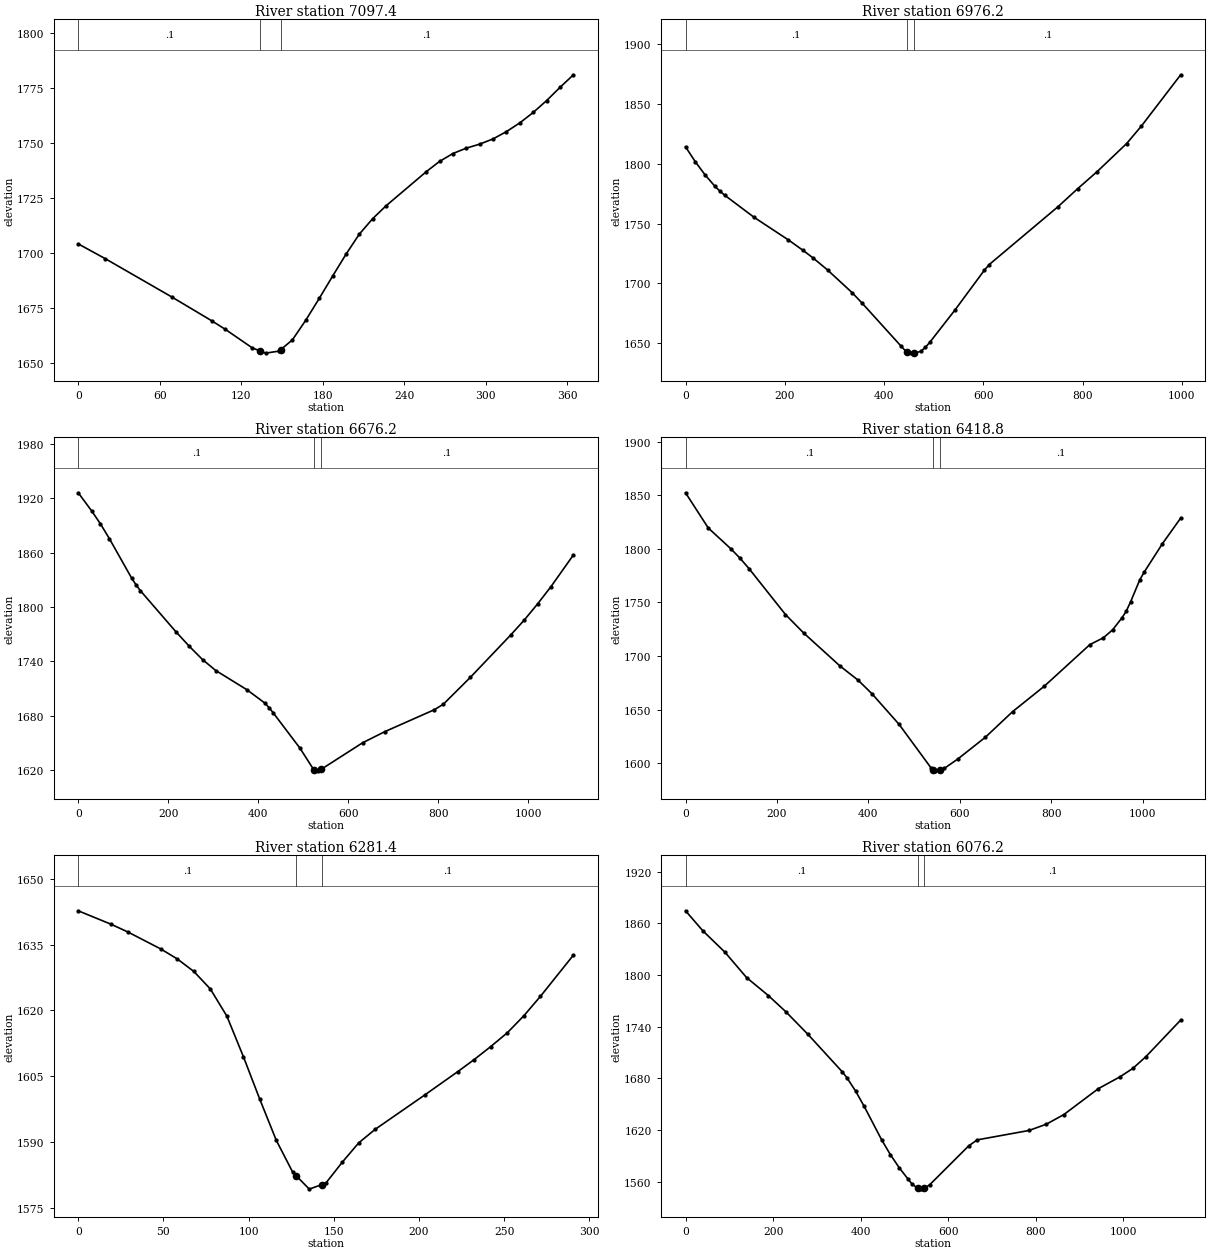
Type RM Length L Ch R = 1 ,7097.4,115.9,121,125.6
XS GIS Cut Line= 2
     1967323.096      347857.664     1967456.562      348196.942
#Sta/Elev= 30
       0 1704.21    19.7 1697.56    69.0 1680.02    98.5 1669.15   108.4 1665.29
   128.1 1656.91   134.1 1655.46   138.0 1654.52   147.8 1655.44   149.1 1656.11
   157.7 1660.58   167.5 1669.48   177.4 1679.38   187.2 1689.49   197.1 1699.48
   206.9 1708.63   216.8 1715.72   226.6 1721.54   256.2 1737.06   266.0 1741.74
   275.9 1745.36   285.8 1747.81   295.6 1749.62   305.5 1752.02   315.3 1755.32
   325.2 1759.32   335.0 1764.03   344.9 1769.45   354.7 1775.43   364.6 1781.16
#Mann= 3 , 0 , 0
       0     0.1       0   134.1   0.045       0   149.1     0.1       0
Bank Sta=   134.1,   149.1
Exp/Cntr=0.3,0.1

Type RM Length L Ch R = 1 ,6976.2,307.1,300,291.9
XS GIS Cut Line= 3
     1967192.679      347572.854     1967259.375      348021.527
     1967351.102      348557.521
#Sta/Elev= 30
       0 1814.11    19.7 1801.63    39.4 1790.66    59.2 1781.17    69.0 1777.20
    78.9 1773.71   138.0 1755.28   207.1 1736.40   236.7 1727.65   256.4 1721.50
   286.0 1711.32   335.3 1692.43   355.0 1683.90   433.9 1647.79   443.7 1643.44
   446.1 1643.05   453.6 1641.84   461.1 1641.87   473.4 1643.30   483.3 1646.67
   493.2 1651.49   542.6 1677.77   601.9 1711.06   611.8 1715.83   750.2 1764.08
   789.8 1779.12   829.3 1793.48   888.6 1816.89   918.3 1831.47   997.4 1874.26
#Mann= 3 , 0 , 0
       0     0.1       0   446.1   0.045       0   461.1     0.1       0
Bank Sta=   446.1,   461.1
Exp/Cntr=0.3,0.1

Type RM Length L Ch R = 1 ,6676.2,263.6,257.4,252.8
XS GIS Cut Line= 3
     1966735.873      347626.074     1966979.225      348099.671
     1967269.371      348588.137
#Sta/Elev= 30
       0 1926.05    29.6 1906.13    49.3 1891.73    69.0 1875.51   118.3 1832.06
   128.2 1824.45   138.0 1817.95   216.9 1772.58   246.5 1756.60   276.1 1741.81
   305.7 1729.67   374.7 1708.52   414.1 1693.96   424.0 1688.79   433.9 1682.58
   493.0 1643.73   522.6 1620.70     525 1620.18   532.5 1618.54     540 1620.56
   632.1 1649.89   682.0 1662.30   791.6 1686.43   811.6 1692.50   871.4 1722.10
   961.1 1768.89   991.0 1785.26  1020.9 1803.24  1050.8 1822.44  1100.6 1857.41
#Mann= 3 , 0 , 0
       0     0.1       0     525   0.045       0     540     0.1       0
Bank Sta=     525,     540
Exp/Cntr=0.3,0.1

Type RM Length L Ch R = 1 ,6418.8,137.2,137.2,137.2
XS GIS Cut Line= 2
     1966431.346      347875.646     1967157.199      348679.388
#Sta/Elev= 30
       0 1852.16    49.7 1819.35    99.4 1799.85   119.2 1791.13   139.1 1781.33
   218.6 1738.62   258.3 1721.44   337.8 1690.65   377.6 1677.34   407.4 1664.90
   467.0 1636.23   536.5 1595.85   541.9 1594.07   546.5 1592.56   556.9 1593.20
   566.3 1595.18   596.1 1604.05   655.8 1624.16   715.4 1648.04   784.9 1671.84
   884.3 1710.55   914.1 1716.99   934.0 1724.29   953.8 1735.10   963.8 1741.57
   973.7 1750.67   993.6 1771.03  1003.5 1778.39  1043.2 1804.77  1083.0 1828.59
#Mann= 3 , 0 , 0
       0     0.1       0   541.9   0.045       0   556.9     0.1       0
Bank Sta=   541.9,   556.9
Exp/Cntr=0.3,0.1

Type RM Length L Ch R = 1 ,6281.4,202.2,204.8,208.7
XS GIS Cut Line= 2
     1966619.593      348286.751     1966814.179      348502.542
#Sta/Elev= 27
       0 1642.73    19.4 1639.64    29.1 1637.90    48.4 1634.03    58.1 1631.75
    67.8 1628.90    77.5 1624.90    87.2 1618.70    96.9 1609.45   106.5 1599.76
   116.2 1590.36   125.9 1583.05     128 1582.22   135.6 1579.22     143 1580.27
   145.3 1580.60   155.0 1585.39   164.6 1589.78   174.3 1592.88   203.4 1600.72
   222.8 1606.05   232.4 1608.80   242.1 1611.76   251.8 1614.90   261.5 1618.77
   271.2 1623.19   290.6 1632.62
#Mann= 3 , 0 , 0
       0     0.1       0     128   0.045       0     143     0.1       0
Bank Sta=     128,     143
Exp/Cntr=0.3,0.1

Type RM Length L Ch R = 1 ,6076.2,303.4,300,294.1
XS GIS Cut Line= 3
     1966209.152      347999.517     1966522.286      348436.493
     1966840.259      348937.496
#Sta/Elev= 30
       0 1874.48    39.8 1851.15    89.6 1826.68   139.4 1797.04   189.2 1776.15
   229.0 1757.44   278.8 1731.60   358.4 1687.47   368.4 1680.95   388.3 1665.51
   408.2 1647.48   448.0 1608.74   467.9 1591.64   487.8 1576.67   507.7 1563.62
   517.7 1557.37   530.1 1552.65   537.6 1551.61   545.1 1552.57   557.4 1556.53
   646.4 1601.60   666.2 1608.74   784.8 1619.68   824.4 1627.01   864.0 1638.06
   943.1 1668.23   992.5 1681.92  1022.2 1691.82  1051.9 1705.47  1131.0 1747.73
#Mann= 3 , 0 , 0
       0     0.1       0   530.1   0.045       0   545.1     0.1       0
Bank Sta=   530.1,   545.1
Exp/Cntr=0.3,0.1

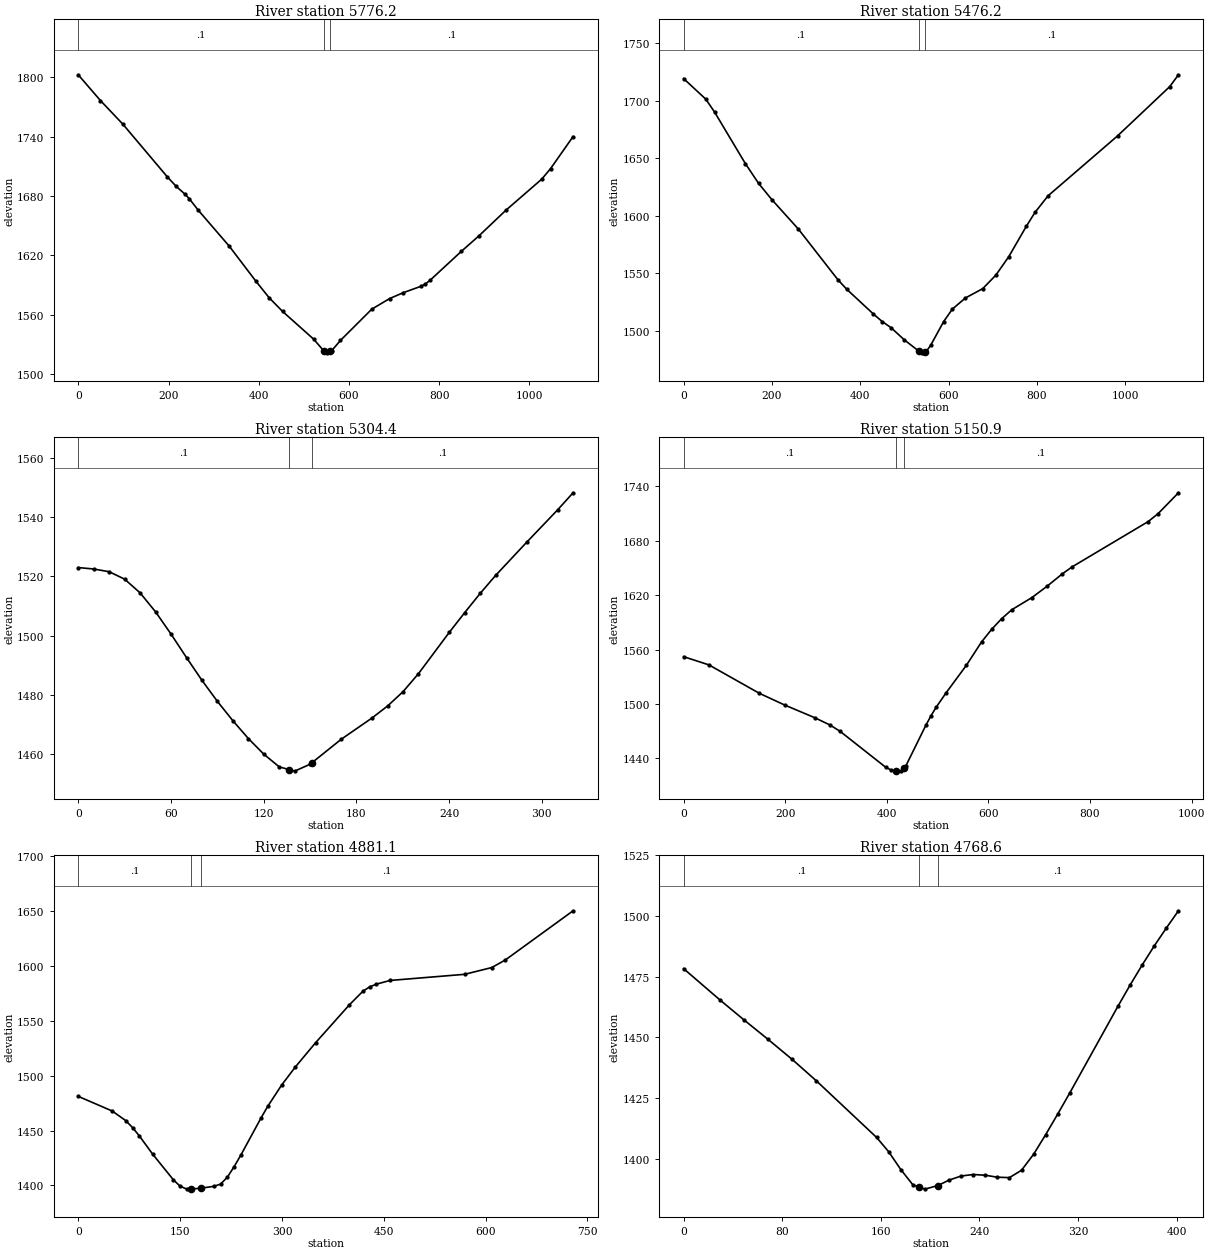
Type RM Length L Ch R = 1 ,5776.2,301.9,299.9,295.7
XS GIS Cut Line= 3
     1965955.274      348276.304     1966339.753      348671.556
     1966739.557      349042.018
#Sta/Elev= 30
       0 1802.34    49.2 1776.32    98.5 1752.66   196.9 1699.52   216.6 1689.87
   236.3 1681.89   246.2 1677.12   265.9 1665.60   334.8 1629.17   393.9 1593.74
   423.4 1577.00   452.9 1563.31   521.9 1535.26   543.9 1523.62   551.4 1521.26
   558.9 1522.99   561.3 1523.55   581.1 1534.12   650.5 1565.67   690.2 1576.41
   719.9 1582.24   759.5 1588.77   769.4 1591.12   779.3 1594.69   848.7 1623.94
   888.4 1639.89   947.8 1665.60  1027.1 1696.97  1046.9 1707.72  1096.5 1739.94
#Mann= 3 , 0 , 0
       0     0.1       0   543.9   0.045       0   558.9     0.1       0
Bank Sta=   543.9,   558.9
Exp/Cntr=0.3,0.1

Type RM Length L Ch R = 1 ,5476.2,183.4,171.8,163.4
XS GIS Cut Line= 3
     1965699.639      348511.791     1966109.912      348862.542
     1966600.715      349173.616
#Sta/Elev= 30
       0 1719.15    50.0 1701.38    70.0 1690.11   139.9 1645.20   169.9 1628.00
   199.9 1613.88   259.9 1588.32   349.8 1544.08   369.8 1535.85   429.8 1514.47
   449.8 1507.89   469.8 1502.58   499.8 1492.01   532.3 1482.29   539.8 1480.43
   547.3 1481.56   549.6 1481.90   559.5 1487.16   589.0 1507.86   608.7 1518.72
   638.3 1528.40   677.6 1536.54   707.2 1548.23   736.7 1564.44   776.1 1590.60
   795.8 1602.76   825.4 1617.21   983.0 1669.38  1101.2 1712.24  1120.8 1722.47
#Mann= 3 , 0 , 0
       0     0.1       0   532.3   0.045       0   547.3     0.1       0
Bank Sta=   532.3,   547.3
Exp/Cntr=0.3,0.1

Type RM Length L Ch R = 1 ,5304.4,154.3,153.4,152.6
XS GIS Cut Line= 2
     1965905.973      348991.501     1966220.304      349053.037
#Sta/Elev= 30
       0 1523.01    10.0 1522.52    20.0 1521.60    30.0 1519.09    40.0 1514.47
    50.0 1508.06    60.1 1500.48    70.1 1492.55    80.1 1484.86    90.1 1477.76
   100.1 1471.23   110.1 1465.22   120.1 1459.93   130.1 1455.64   136.4 1454.73
   140.1 1454.20   150.1 1456.54   151.4 1457.09   170.2 1464.96   190.2 1472.18
   200.2 1476.20   210.2 1481.03   220.2 1487.12   240.2 1501.12   250.2 1507.80
   260.2 1514.28   270.2 1520.36   290.3 1531.57   310.3 1542.50   320.3 1548.27
#Mann= 3 , 0 , 0
       0     0.1       0   136.4   0.045       0   151.4     0.1       0
Bank Sta=   136.4,   151.4
Exp/Cntr=0.3,0.1

Type RM Length L Ch R = 1 ,5150.9,251.8,269.5,287.1
XS GIS Cut Line= 2
     1965607.164      349105.148     1966569.559      349254.907
#Sta/Elev= 30
       0 1552.12    49.7 1543.09   149.1 1511.74   198.8 1498.88   258.4 1484.80
   288.2 1476.82   308.1 1469.83   397.5 1430.40   407.5 1427.49   417.4 1426.03
   418.7 1426.04   427.4 1426.08   433.7 1429.61   437.3 1431.62   477.0 1476.74
   487.0 1487.07   496.9 1496.26   516.8 1512.42   556.6 1542.63   586.4 1568.33
   606.2 1582.17   626.1 1594.02   646.0 1603.86   685.8 1617.31   715.6 1629.82
   745.4 1643.35   765.3 1651.27   914.4 1700.94   934.2 1709.81   974.0 1732.65
#Mann= 3 , 0 , 0
       0     0.1       0   418.7   0.045       0   433.7     0.1       0
Bank Sta=   418.7,   433.7
Exp/Cntr=0.3,0.1

Type RM Length L Ch R = 1 ,4881.1,115.6,112.6,109.6
XS GIS Cut Line= 2
     1965775.695      349224.894     1966208.497      349811.118
#Sta/Elev= 30
       0 1481.09    49.9 1467.78    69.9 1459.04    79.9 1452.68    89.8 1445.21
   109.8 1428.30   139.8 1405.35   149.7 1399.50   159.7 1396.67   166.1 1396.71
   181.1 1397.58   199.6 1399.20   209.6 1401.23   219.6 1407.58   229.6 1417.19
   239.6 1427.84   269.5 1461.82   279.5 1472.48   299.5 1491.38   319.4 1507.60
   349.4 1529.84   399.3 1564.42   419.2 1576.79   429.2 1580.75   439.2 1583.25
   459.2 1586.59   569.0 1592.17   608.9 1598.32   628.9 1605.18   728.7 1649.96
#Mann= 3 , 0 , 0
       0     0.1       0   166.1   0.045       0   181.1     0.1       0
Bank Sta=   166.1,   181.1
Exp/Cntr=0.3,0.1

Type RM Length L Ch R = 1 ,4768.6,73.3,71.7,70.1
XS GIS Cut Line= 2
     1965644.169      349279.638     1965923.574      349567.775
#Sta/Elev= 30
       0 1478.30    29.4 1465.43    49.0 1457.16    68.5 1449.15    88.1 1440.87
   107.7 1432.04   156.6 1408.69   166.4 1402.78   176.2 1395.45   186.0 1389.16
   191.3 1388.21   195.8 1387.40   206.3 1388.89   215.4 1391.14   225.2 1392.81
   234.9 1393.43   244.7 1393.13   254.5 1392.32   264.3 1392.14   274.1 1395.18
   283.9 1401.76   293.7 1409.86   303.5 1418.37   313.3 1427.09   352.4 1462.86
   362.2 1471.54   372.0 1479.82   381.8 1487.69   391.6 1495.06   401.4 1502.16
#Mann= 3 , 0 , 0
       0     0.1       0   191.3   0.045       0   206.3     0.1       0
Bank Sta=   191.3,   206.3
Exp/Cntr=0.3,0.1

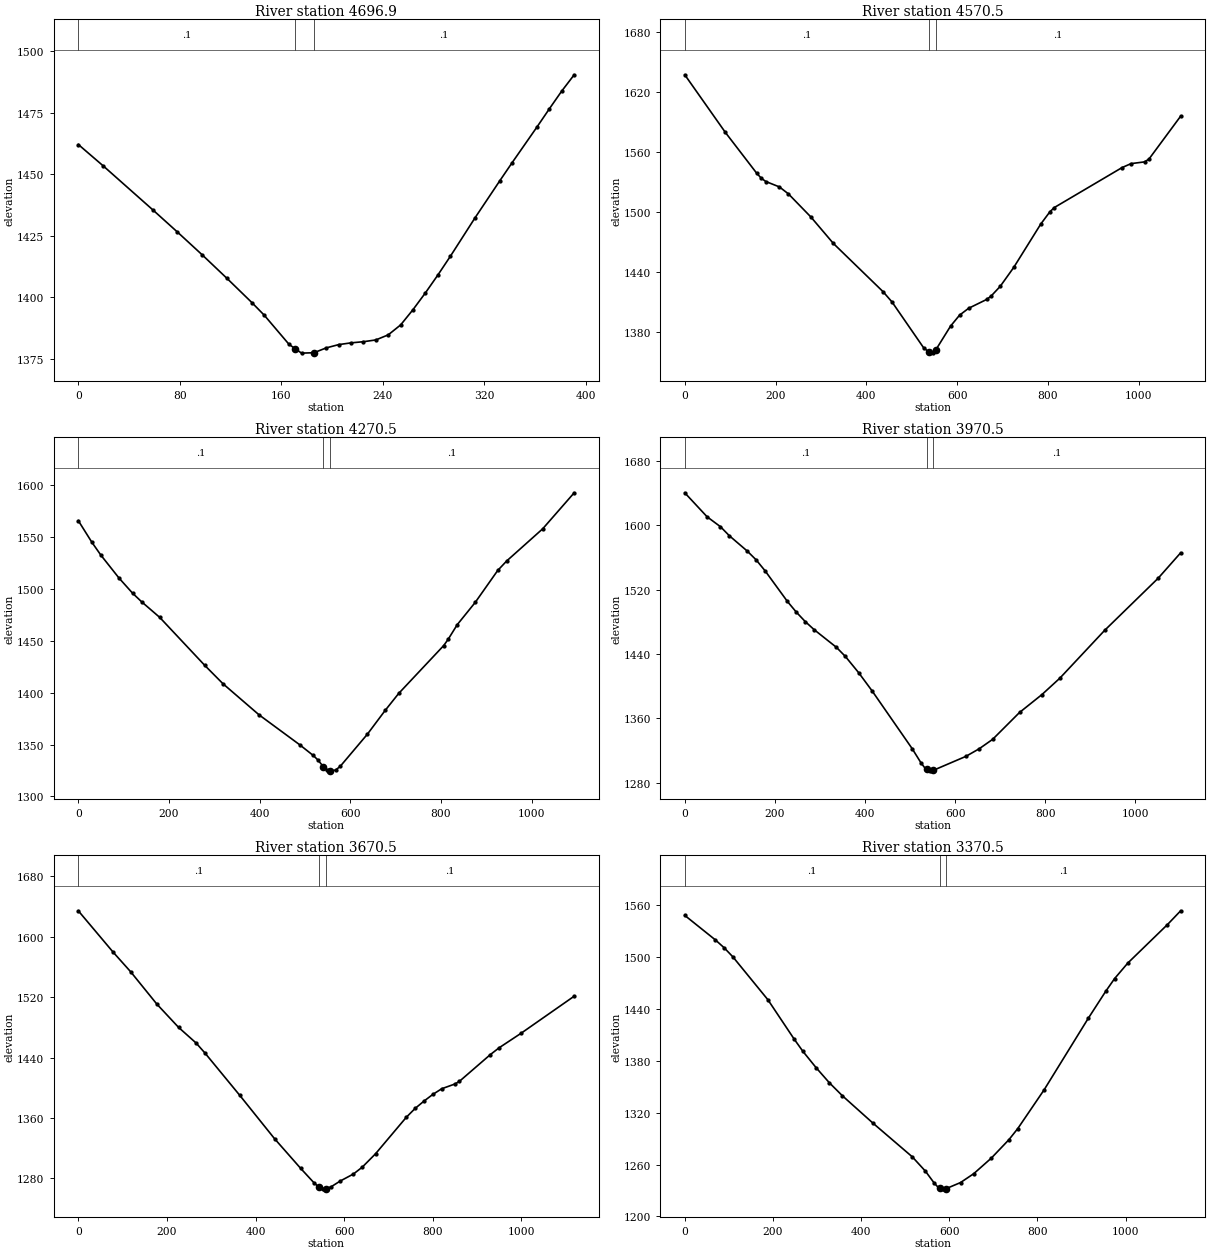
Type RM Length L Ch R = 1 ,4696.9,124.4,126.4,129.4
XS GIS Cut Line= 2
     1965599.958      349354.063     1965891.005      349615.174
#Sta/Elev= 30
       0 1462.17    19.6 1453.49    58.6 1435.67    78.2 1426.57    97.8 1417.27
   117.3 1407.72   136.8 1397.95   146.6 1392.80   166.2 1380.92   170.8 1379.26
   176.0 1377.38   185.8 1377.54   195.5 1379.51   205.3 1380.84   215.0 1381.55
   224.8 1382.02   234.6 1382.74   244.4 1384.81   254.2 1388.86   263.9 1395.04
   273.7 1401.87   283.5 1409.11   293.3 1416.68   312.8 1432.35   332.4 1447.46
   342.1 1454.80   361.7 1469.30   371.5 1476.72   381.2 1483.89   391.0 1490.49
#Mann= 3 , 0 , 0
       0     0.1       0   170.8   0.045       0   185.8     0.1       0
Bank Sta=   170.8,   185.8
Exp/Cntr=0.3,0.1

Type RM Length L Ch R = 1 ,4570.5,296.3,299.9,300.2
XS GIS Cut Line= 3
     1965271.474      349166.520     1965646.282      349563.375
     1966002.220      349978.374
#Sta/Elev= 30
       0 1636.78    89.3 1579.32   158.8 1538.30   168.7 1533.47   178.6 1530.23
   208.4 1524.86   228.3 1517.90   277.9 1494.78   327.5 1468.34   436.7 1420.31
   456.6 1409.97   526.0 1364.38   538.4 1359.79   545.9 1358.86   553.4 1362.32
   585.6 1385.82   605.5 1396.78   625.4 1403.63   665.2 1412.47   675.1 1415.91
   695.0 1425.51   724.8 1444.42   784.4 1487.75   804.3 1499.88   814.3 1504.26
   963.4 1544.12   983.3 1548.10  1013.1 1549.84  1023.0 1552.75  1092.6 1595.45
#Mann= 3 , 0 , 0
       0     0.1       0   538.4   0.045       0   553.4     0.1       0
Bank Sta=   538.4,   553.4
Exp/Cntr=0.3,0.1

Type RM Length L Ch R = 1 ,4270.5,298.1,300,302
XS GIS Cut Line= 3
     1965115.780      349309.547     1965423.134      349763.336
     1965772.440      350182.503
#Sta/Elev= 30
       0 1565.67    29.9 1544.87    49.8 1532.45    89.7 1510.43   119.6 1495.86
   139.5 1487.59   179.4 1472.57   279.0 1426.23   318.9 1408.66   398.6 1378.64
   488.3 1349.80   518.2 1339.47   528.2 1335.27   540.6 1328.64   548.1 1325.36
   555.6 1324.63   558.0 1324.40   567.9 1325.56   577.8 1329.07   637.4 1359.87
   677.0 1382.99   706.8 1399.31   806.0 1445.40   815.9 1451.50   835.8 1465.50
   875.5 1486.97   925.1 1517.74   944.9 1526.89  1024.3 1557.86  1093.7 1592.53
#Mann= 3 , 0 , 0
       0     0.1       0   540.6   0.045       0   555.6     0.1       0
Bank Sta=   540.6,   555.6
Exp/Cntr=0.3,0.1

Type RM Length L Ch R = 1 ,3970.5,297.6,300,300
XS GIS Cut Line= 3
     1964886.928      349421.695     1965154.718      349895.478
     1965470.276      350353.323
#Sta/Elev= 30
       0 1640.26    49.5 1610.48    79.2 1598.14    99.0 1586.87   138.5 1567.95
   158.3 1556.98   178.1 1543.42   227.6 1505.37   247.4 1492.06   267.2 1480.34
   287.0 1470.26   336.4 1448.33   356.2 1437.06   385.9 1416.73   415.6 1394.20
   504.6 1322.37   524.4 1304.56   534.3 1297.30   536.7 1296.62   544.2 1294.48
   551.7 1295.53   623.7 1312.80   653.4 1322.29   683.2 1334.00   742.8 1367.35
   792.5 1389.58   832.2 1409.92   931.5 1469.27  1050.6 1534.24  1100.3 1565.69
#Mann= 3 , 0 , 0
       0     0.1       0   536.7   0.045       0   551.7     0.1       0
Bank Sta=   536.7,   551.7
Exp/Cntr=0.3,0.1

Type RM Length L Ch R = 1 ,3670.5,309.3,299.4,292
XS GIS Cut Line= 3
     1964697.926      349555.209     1964918.041      350060.383
     1965232.635      350533.139
#Sta/Elev= 30
       0 1634.21    78.7 1579.39   118.1 1553.54   177.1 1510.79   226.3 1479.86
   265.7 1459.25   285.4 1446.21   364.1 1390.07   442.8 1332.54   501.8 1293.21
   531.4 1274.42   543.5 1267.97   551.0 1265.78   558.5 1266.18   571.0 1269.08
   590.9 1276.47   620.8 1285.80   640.7 1294.86   670.6 1312.53   740.3 1361.02
   760.3 1372.76   780.2 1382.40   800.1 1391.22   820.0 1398.67   849.9 1404.97
   859.9 1408.44   929.6 1443.79   949.5 1452.87   999.4 1472.22  1118.9 1521.17
#Mann= 3 , 0 , 0
       0     0.1       0   543.5   0.045       0   558.5     0.1       0
Bank Sta=   543.5,   558.5
Exp/Cntr=0.3,0.1

Type RM Length L Ch R = 1 ,3370.5,295.2,299.8,307.6
XS GIS Cut Line= 3
     1964306.613      349872.233     1964742.065      350263.573
     1965172.517      350588.337
#Sta/Elev= 30
       0 1548.48    69.5 1520.07    89.3 1511.01   109.2 1500.42   188.5 1450.84
   248.1 1405.26   267.9 1391.10   297.7 1372.28   327.5 1354.94   357.2 1339.80
   426.7 1308.02   516.0 1268.97   545.8 1252.38   565.6 1238.68   575.5 1233.20
     578 1232.79   585.5 1231.57     593 1232.19   625.4 1239.16   655.4 1249.45
   695.3 1267.48   735.2 1288.81   755.2 1301.62   815.1 1346.58   915.0 1429.20
   954.9 1460.70   974.9 1475.32  1004.9 1493.33  1094.7 1537.81  1124.7 1553.80
#Mann= 3 , 0 , 0
       0     0.1       0     578   0.045       0     593     0.1       0
Bank Sta=     578,     593
Exp/Cntr=0.3,0.1