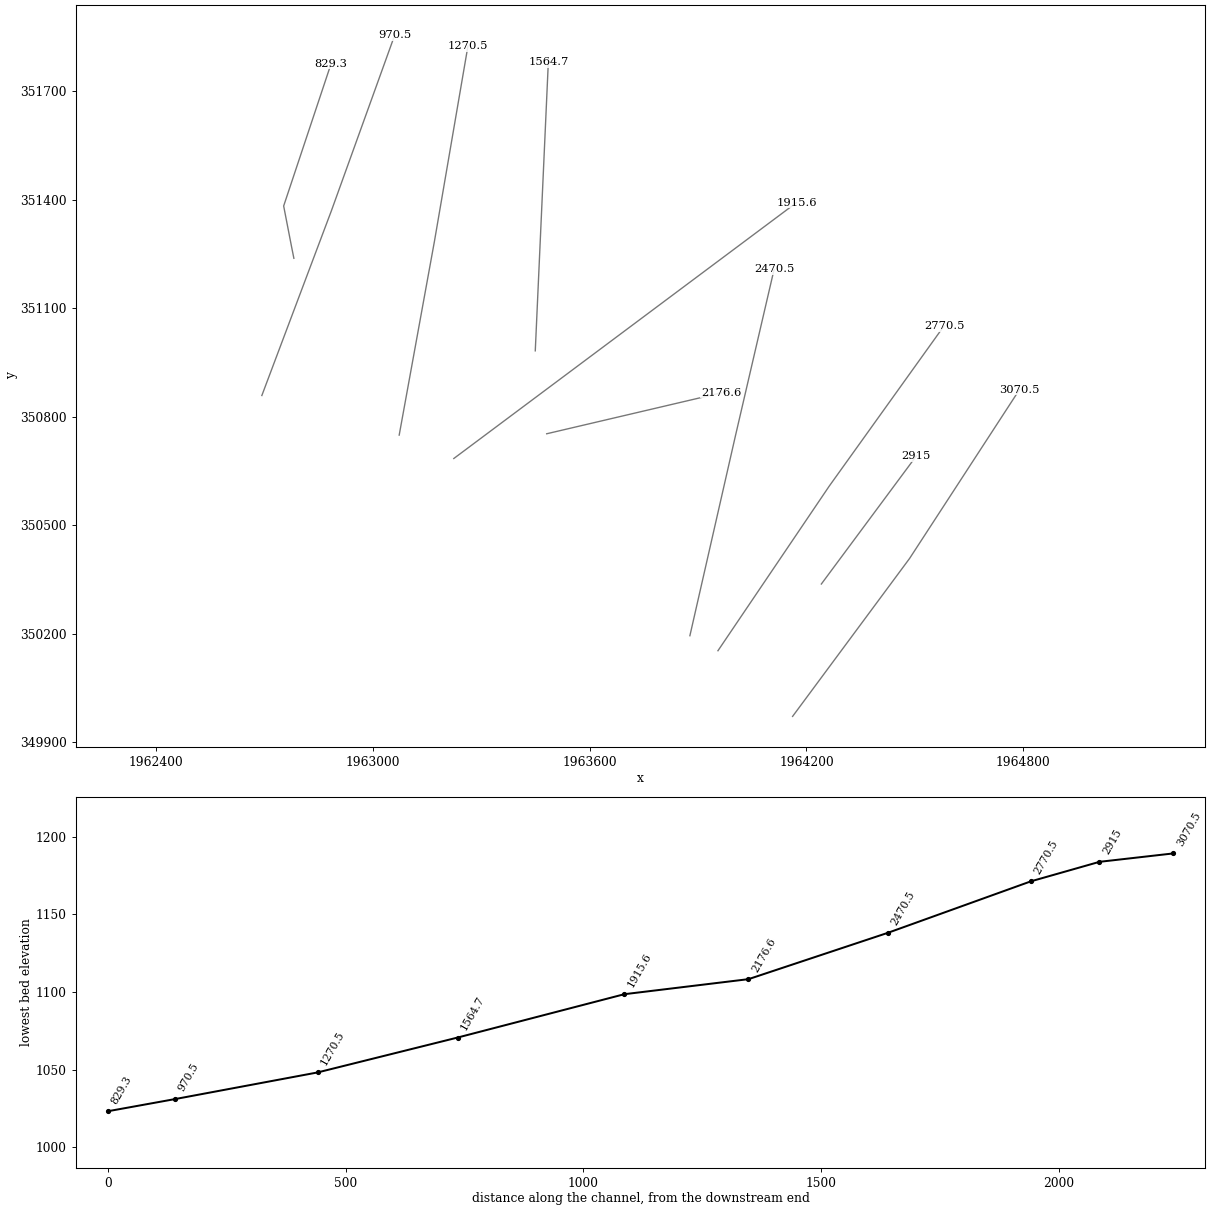
HEC-RAS study EphrmCrk.prj: EphrmCrk

--- EphrmCrk.g01 (geometry) --- (continued)

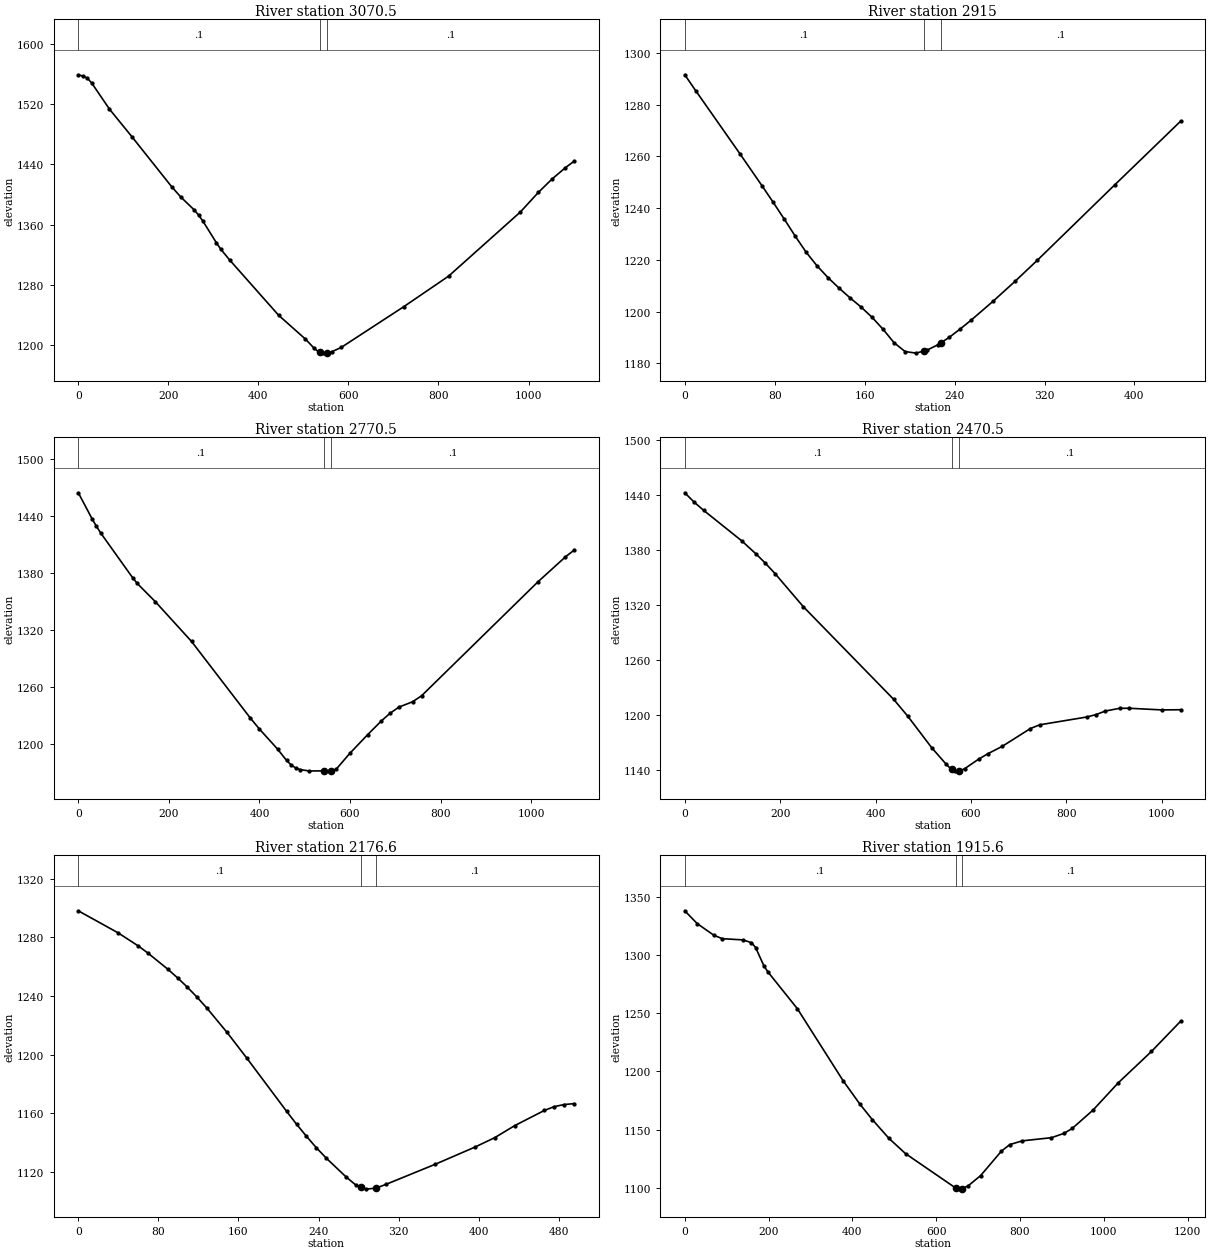
Type RM Length L Ch R = 1 ,3070.5,155.5,155.5,154.1
XS GIS Cut Line= 3
     1964161.598      349970.632     1964485.390      350407.752
     1964789.494      350874.938
#Sta/Elev= 30
       0 1558.84     9.9 1557.23    19.8 1554.49    29.7 1547.97    69.2 1513.25
   118.7 1476.90   207.7 1410.02   227.5 1396.67   257.2 1379.60   267.0 1372.71
   276.9 1364.44   306.6 1335.94   316.5 1327.25   336.3 1312.89   445.1 1239.51
   504.4 1208.02   524.2 1195.60   534.1 1190.86   536.5 1190.49   544.0 1189.35
   551.5 1189.95   563.9 1191.46   583.8 1196.83   723.2 1251.13   822.7 1291.67
   982.0 1376.77  1021.8 1402.67  1051.6 1420.14  1081.5 1435.33  1101.4 1444.17
#Mann= 3 , 0 , 0
       0     0.1       0   536.5   0.045       0   551.5     0.1       0
Bank Sta=   536.5,   551.5
Exp/Cntr=0.3,0.1

Type RM Length L Ch R = 1 ,2915,143.3,144.3,144.7
XS GIS Cut Line= 2
     1964241.183      350336.971     1964503.957      350691.217
#Sta/Elev= 30
       0 1291.54     9.8 1285.35    49.0 1261.04    68.6 1248.70    78.4 1242.40
    88.2 1235.94    98.0 1229.32   107.8 1223.04   117.6 1217.70   127.4 1213.14
   137.2 1209.08   147.0 1205.31   156.8 1201.76   166.6 1197.79   176.4 1193.14
   186.2 1187.94   196.0 1184.54   205.8 1183.93   212.6 1184.74   215.6 1185.10
   225.4 1187.22   227.6 1187.85   235.2 1190.01   245.0 1193.27   254.8 1196.70
   274.4 1204.05   294.0 1211.77   313.6 1219.83   382.3 1248.91   441.1 1273.61
#Mann= 3 , 0 , 0
       0     0.1       0   212.6   0.045       0   227.6     0.1       0
Bank Sta=   212.6,   227.6
Exp/Cntr=0.3,0.1

Type RM Length L Ch R = 1 ,2770.5,291.8,300.2,309.1
XS GIS Cut Line= 3
     1963955.062      350152.366     1964263.036      350607.933
     1964580.608      351051.104
#Sta/Elev= 30
       0 1464.01    30.0 1437.00    40.0 1428.81    50.0 1421.38   120.0 1374.68
   130.0 1368.76   170.0 1349.59   250.0 1307.74   379.9 1227.16   399.9 1215.64
   439.9 1194.61   459.9 1182.60   469.9 1177.92   479.9 1174.72   489.9 1172.97
   509.9 1171.52   542.4 1171.65   557.4 1171.38   559.8 1171.36   569.7 1173.48
   599.5 1189.98   639.1 1209.74   668.8 1223.93   688.7 1232.29   708.5 1238.77
   738.2 1244.30   758.1 1250.59  1015.8 1370.73  1075.3 1396.43  1095.1 1403.81
#Mann= 3 , 0 , 0
       0     0.1       0   542.4   0.045       0   557.4     0.1       0
Bank Sta=   542.4,   557.4
Exp/Cntr=0.3,0.1

Type RM Length L Ch R = 1 ,2470.5,319,293.6,268.4
XS GIS Cut Line= 3
     1963877.397      350193.905     1964003.409      350746.946
     1964110.350      351207.341
#Sta/Elev= 30
       0 1441.85    19.9 1431.56    39.8 1422.61   119.4 1389.48   149.3 1375.22
   169.2 1364.96   189.1 1353.84   248.8 1317.50   437.8 1216.70   467.7 1198.14
   517.5 1164.01   547.3 1146.30   557.3 1141.05   559.7 1140.37   567.2 1138.25
   574.7 1138.42   577.1 1138.47   586.9 1140.90   616.4 1151.37   636.1 1157.37
   665.7 1165.25   724.8 1184.71   744.5 1188.79   842.9 1197.28   862.6 1199.95
   882.3 1203.83   911.9 1206.77   931.6 1206.85  1000.5 1205.03  1039.9 1205.23
#Mann= 3 , 0 , 0
       0     0.1       0   559.7   0.045       0   574.7     0.1       0
Bank Sta=   559.7,   574.7
Exp/Cntr=0.3,0.1

Type RM Length L Ch R = 1 ,2176.6,251.7,261,270.3
XS GIS Cut Line= 2
     1963481.134      350752.753     1963963.440      350865.846
#Sta/Elev= 30
       0 1298.03    39.6 1283.08    59.4 1274.32    69.4 1269.31    89.2 1258.35
    99.1 1252.39   109.0 1245.96   118.9 1238.98   128.8 1231.46   148.6 1215.14
   168.4 1197.59   208.1 1161.37   218.0 1152.62   227.9 1144.38   237.8 1136.58
   247.7 1129.48   267.5 1116.68   277.4 1111.05   282.3 1109.71   287.3 1108.35
   297.3 1109.02   307.1 1111.51   356.7 1125.32   396.3 1137.01   416.1 1143.44
   435.9 1151.60   465.7 1162.01   475.6 1164.60   485.5 1166.00   495.4 1166.63
#Mann= 3 , 0 , 0
       0     0.1       0   282.3   0.045       0   297.3     0.1       0
Bank Sta=   282.3,   297.3
Exp/Cntr=0.3,0.1

Type RM Length L Ch R = 1 ,1915.6,330.8,350.8,370.8
XS GIS Cut Line= 2
     1963224.112      350684.314     1964172.376      351392.415
#Sta/Elev= 30
       0 1338.28    29.8 1327.23    69.6 1317.20    89.5 1314.30   139.2 1313.24
   159.1 1310.85   169.1 1306.67   189.0 1290.71   198.9 1285.46   268.5 1254.10
   377.9 1191.99   417.7 1171.97   447.5 1158.54   487.3 1142.35   527.1 1129.16
   646.6 1099.61   656.4 1098.66   661.6 1099.07   676.3 1101.49   706.1 1110.29
   755.8 1131.40   775.7 1137.02   805.6 1140.23   875.2 1142.96   905.0 1146.65
   924.9 1150.96   974.6 1166.77  1034.3 1190.07  1113.9 1217.20  1183.5 1243.22
#Mann= 3 , 0 , 0
       0     0.1       0   646.6   0.045       0   661.6     0.1       0
Bank Sta=   646.6,   661.6
Exp/Cntr=0.3,0.1

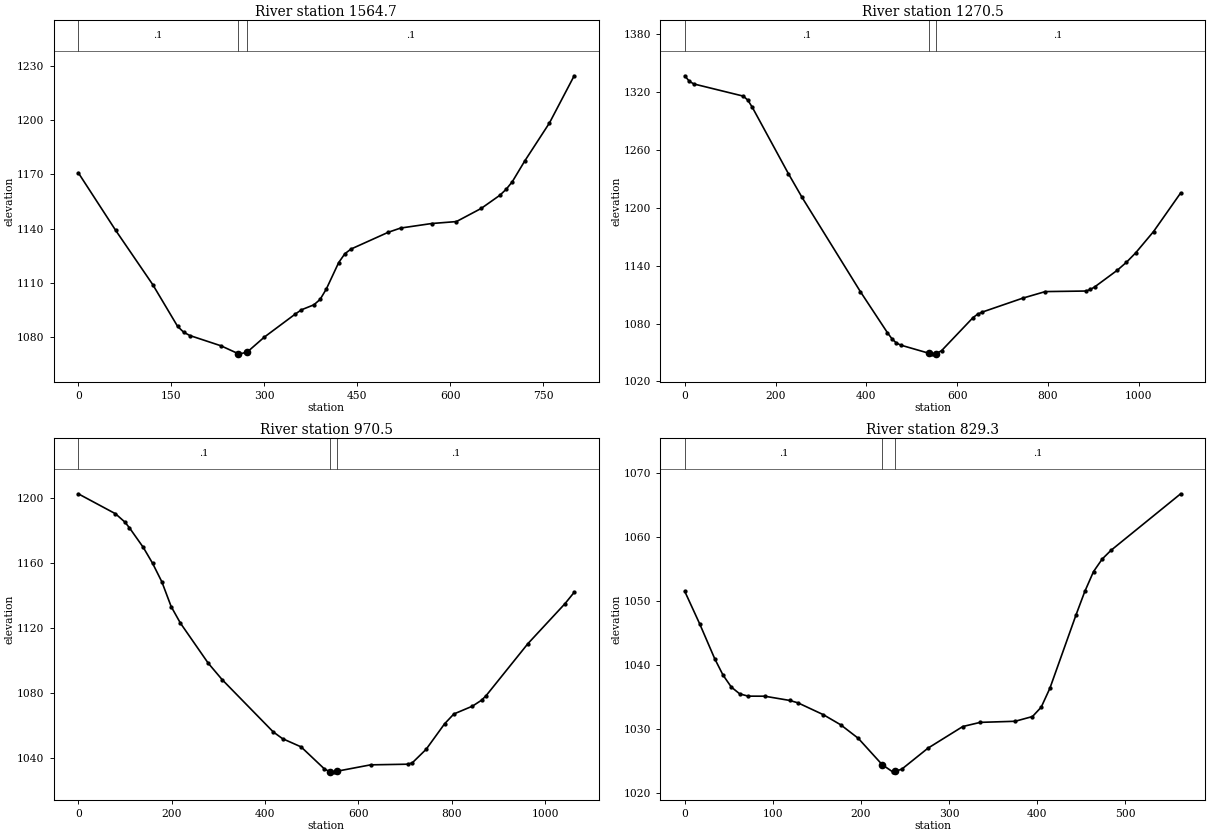
Type RM Length L Ch R = 1 ,1564.7,297.2,294.1,291.3
XS GIS Cut Line= 2
     1963449.534      350982.265     1963485.671      351781.182
#Sta/Elev= 30
       0 1170.90    60.0 1139.22   120.0 1109.14   160.0 1086.12   169.9 1082.82
   179.9 1080.99   229.9 1075.34   257.7 1071.00   259.9 1070.72   272.7 1071.96
   299.9 1080.10   349.9 1092.86   359.9 1095.22   379.9 1097.96   389.9 1100.93
   399.9 1106.64   419.9 1121.30   429.9 1126.20   439.8 1128.78   499.8 1138.04
   519.8 1140.38   569.8 1142.88   609.8 1143.96   649.8 1151.23   679.8 1158.48
   689.8 1161.72   699.8 1165.91   719.8 1177.33   759.8 1198.42   799.7 1224.49
#Mann= 3 , 0 , 0
       0     0.1       0   257.7   0.045       0   272.7     0.1       0
Bank Sta=   257.7,   272.7
Exp/Cntr=0.3,0.1

Type RM Length L Ch R = 1 ,1270.5,304.1,300.1,296.1
XS GIS Cut Line= 3
     1963072.956      350749.078     1963170.629      351286.106
     1963263.096      351824.962
#Sta/Elev= 30
       0 1336.90     9.9 1331.30    19.8 1328.48   129.0 1315.84   138.9 1311.66
   148.9 1304.15   228.3 1235.42   258.0 1211.13   387.0 1113.02   446.6 1070.44
   456.5 1064.16   466.4 1059.73   476.4 1057.55   538.3 1049.11   545.8 1048.27
   553.3 1048.64   565.7 1051.80   635.3 1086.22   645.2 1089.64   655.2 1091.84
   744.6 1106.31   794.4 1113.13   883.8 1113.71   893.8 1115.32   903.7 1118.14
   953.4 1135.40   973.3 1143.58   993.2 1153.11  1032.9 1175.37  1092.6 1215.38
#Mann= 3 , 0 , 0
       0     0.1       0   538.3   0.045       0   553.3     0.1       0
Bank Sta=   538.3,   553.3
Exp/Cntr=0.3,0.1

Type RM Length L Ch R = 1 ,970.5,138.1,141,144.2
XS GIS Cut Line= 3
     1962692.877      350858.611     1962885.534      351370.411
     1963060.362      351855.406
#Sta/Elev= 30
       0 1202.83    79.5 1190.55    99.4 1185.50   109.4 1181.91   139.2 1169.76
   159.1 1159.96   179.0 1148.50   198.9 1133.26   218.7 1123.06   278.4 1098.29
   308.2 1088.15   417.6 1055.91   437.5 1051.75   477.3 1046.67   527.0 1033.13
   539.4 1031.19   546.9 1031.09   554.4 1031.66   626.2 1035.58   705.5 1035.98
   715.4 1036.78   745.2 1045.16   784.8 1060.92   804.6 1066.97   844.3 1071.78
   864.1 1075.50   874.0 1078.37   963.3 1110.38  1042.6 1135.00  1062.4 1142.04
#Mann= 3 , 0 , 0
       0     0.1       0   539.4   0.045       0   554.4     0.1       0
Bank Sta=   539.4,   554.4
Exp/Cntr=0.3,0.1

Type RM Length L Ch R = 1 ,829.3,824.3,829.1,833.3
XS GIS Cut Line= 4
     1962781.511      351238.386     1962774.859      351271.649
     1962753.238      351383.078     1962884.625      351777.239
#Sta/Elev= 30
       0 1051.52    17.0 1046.42    33.9 1041.02    43.4 1038.44    52.8 1036.57
    62.3 1035.51    71.8 1035.15    90.7 1035.14   119.0 1034.48   128.5 1034.10
   157.3 1032.25   177.1 1030.66   196.9 1028.56   224.2 1024.42   236.5 1023.27
   239.2 1023.40   246.4 1023.74   276.0 1027.01   315.6 1030.40   335.4 1031.05
   375.0 1031.22   394.7 1031.96   404.6 1033.42   414.5 1036.39   444.2 1047.87
   454.1 1051.51   464.0 1054.62   473.9 1056.59   483.8 1057.94   562.9 1066.78
#Mann= 3 , 0 , 0
       0     0.1       0   224.2   0.045       0   239.2     0.1       0
Bank Sta=   224.2,   239.2
Exp/Cntr=0.3,0.1